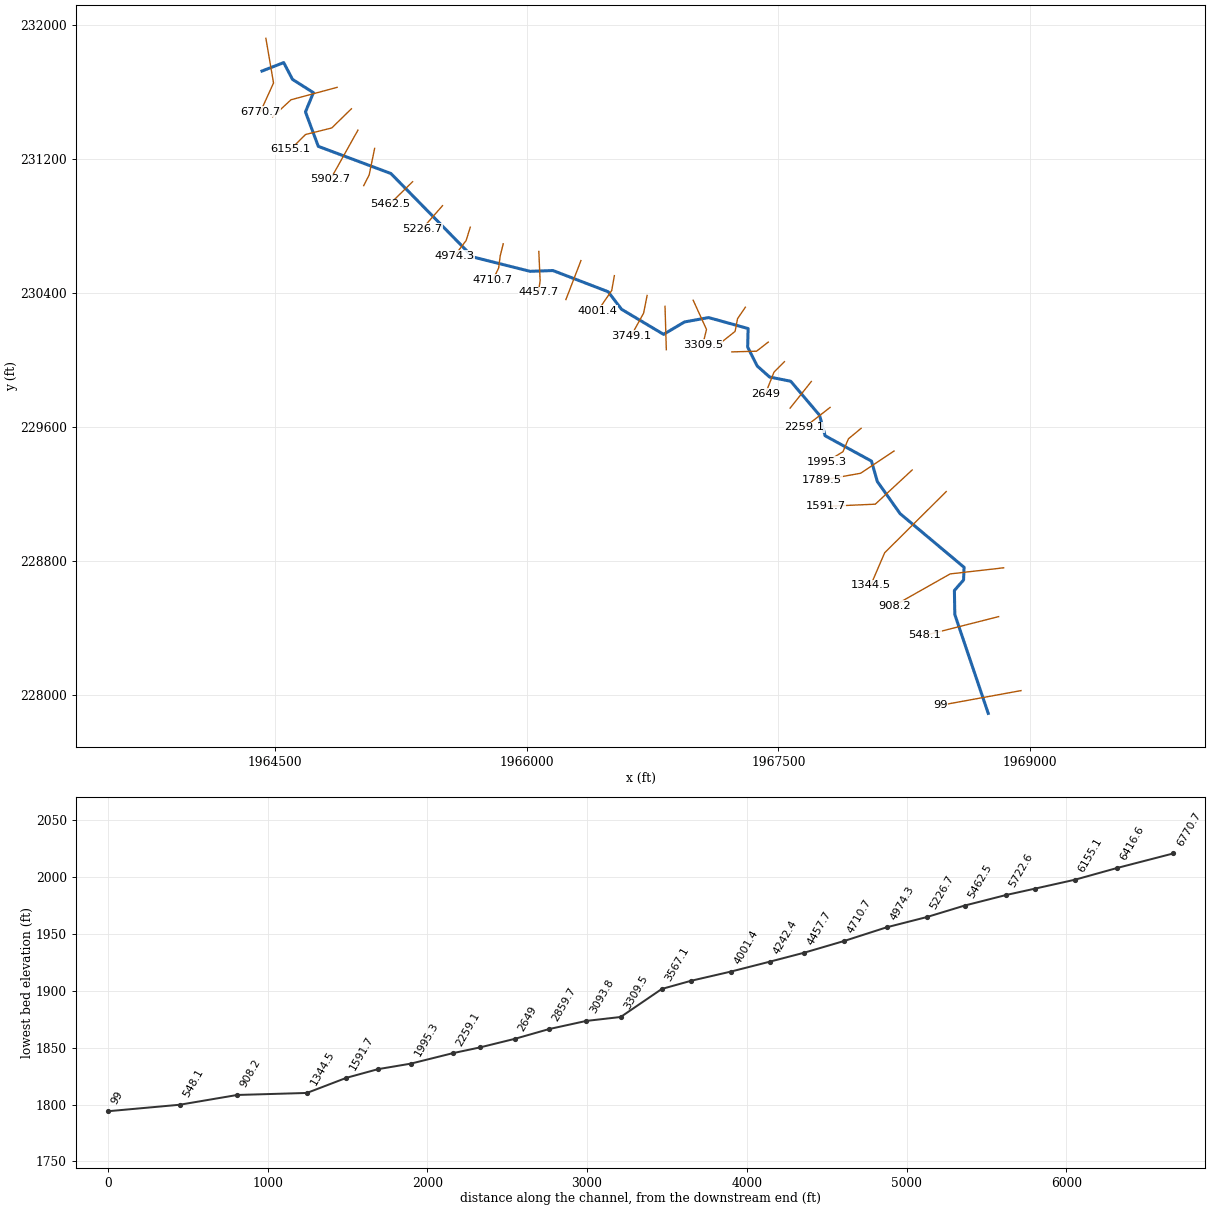
--- WHOAKBR.prj (project) ---

Proj Title=WHOAKBR
Current Plan=p01
Default Exp/Contr=0,0
English Units
Geom File=g01
Flow File=f01
Plan File=p01
BEGIN DESCRIPTION:
END DESCRIPTION:
DSS Export Rating Curves= 0
DSS Export Rating Curve Sorted= 0
DSS Export Volume Flow Curves= 0
DXF OffsetX= 0
DXF OffsetY= 0
DXF ScaleX= 0
DXF ScaleY= 0

--- WHOAKBR.p01 (plan) ---

Plan Title=Floodplain
Program Version=4.00
Geom File=g01
Flow File=f01
K Sum by GR=0
Std Step Tol=0.01
Critical Tol=0.01
Num of Std Step Trials=20
Max Error Tol=0.3
Flow Tol Ratio=0.001
Split Flow NTrial=30
Split Flow Tol=0.02
Split Flow Ratio=0.02
Log Output Level=0
Friction Slope Method=1
Unsteady Friction Slope Method=2
Unsteady Bridges Friction Slope Method=1
Global Log Level=0
CheckData=False
Run HTab=0
Run UNet=0
Run PostProcess=0
UNET Theta=0
UNET Theta Warmup=0
UNET ZTol=0
UNET ZSATol=0
UNET MxIter=0
UNET MaxInSteps=0
UNET DtIC=0
UNET DtMin=0
UNET MaxCRTS=0
UNET WFStab=0
UNET SFStab=0
UNET WFX=0
UNET SFX=0
UNET DSS MLevel=0
UNET DZMax Abort=0
UNET Convert EG Bridges=0
UNET Use Existing IB Tables=0
UNET Froude Limit=0
UNET Froude Power=0
Write IC File=0
Echo Input=False
Echo Output=False
Write Detailed=0

--- WHOAKBR.f01 (steady flow) ---

Flow Title=2010 USGS WV Regression Equation
Program Version=4.00
Number of Profiles=1
Profile Names=P100yr
River Rch & RM=WHOAKBR,Main      ,6770.7
546.6745
River Rch & RM=WHOAKBR,Main      ,4001.4
592.4487
River Rch & RM=WHOAKBR,Main      ,1789.5
638.9031
River Rch & RM=WHOAKBR,Main      ,1344.5
639.0439
Boundary for River Rch & Prof#=WHOAKBR,Main      ,1
Up Type=0
Dn Type=3
Dn Slope=0.019697

--- WHOAKBR.g01 (geometry) ---

Geom Title=LiDAR
Program Version=4.10

River Reach=WHOAKBR         ,Main
Reach XY= 30
     1964420.274      231726.371     1964549.973      231776.809
     1964602.377      231676.587      1964727.02      231597.348
     1964679.672      231482.039     1964756.313      231276.354
     1965189.342      231113.962     1965677.306      230615.414
      1966019.24      230529.603     1966155.489      230534.188
      1966484.85      230407.631     1966564.237      230302.957
      1966815.12      230152.952     1966940.233      230226.972
     1967083.688      230253.174     1967319.505      230187.669
     1967316.838      230076.598     1967373.874      229963.643
      1967447.48      229897.996     1967573.662      229872.592
     1967745.939      229668.873     1967778.691      229547.035
     1968055.336      229395.392     1968090.275      229273.095
     1968226.087      229081.297     1968607.463       228760.64
      1968604.28      228685.108      1968549.68      228622.111
     1968552.118      228478.674     1968751.453       227887.92

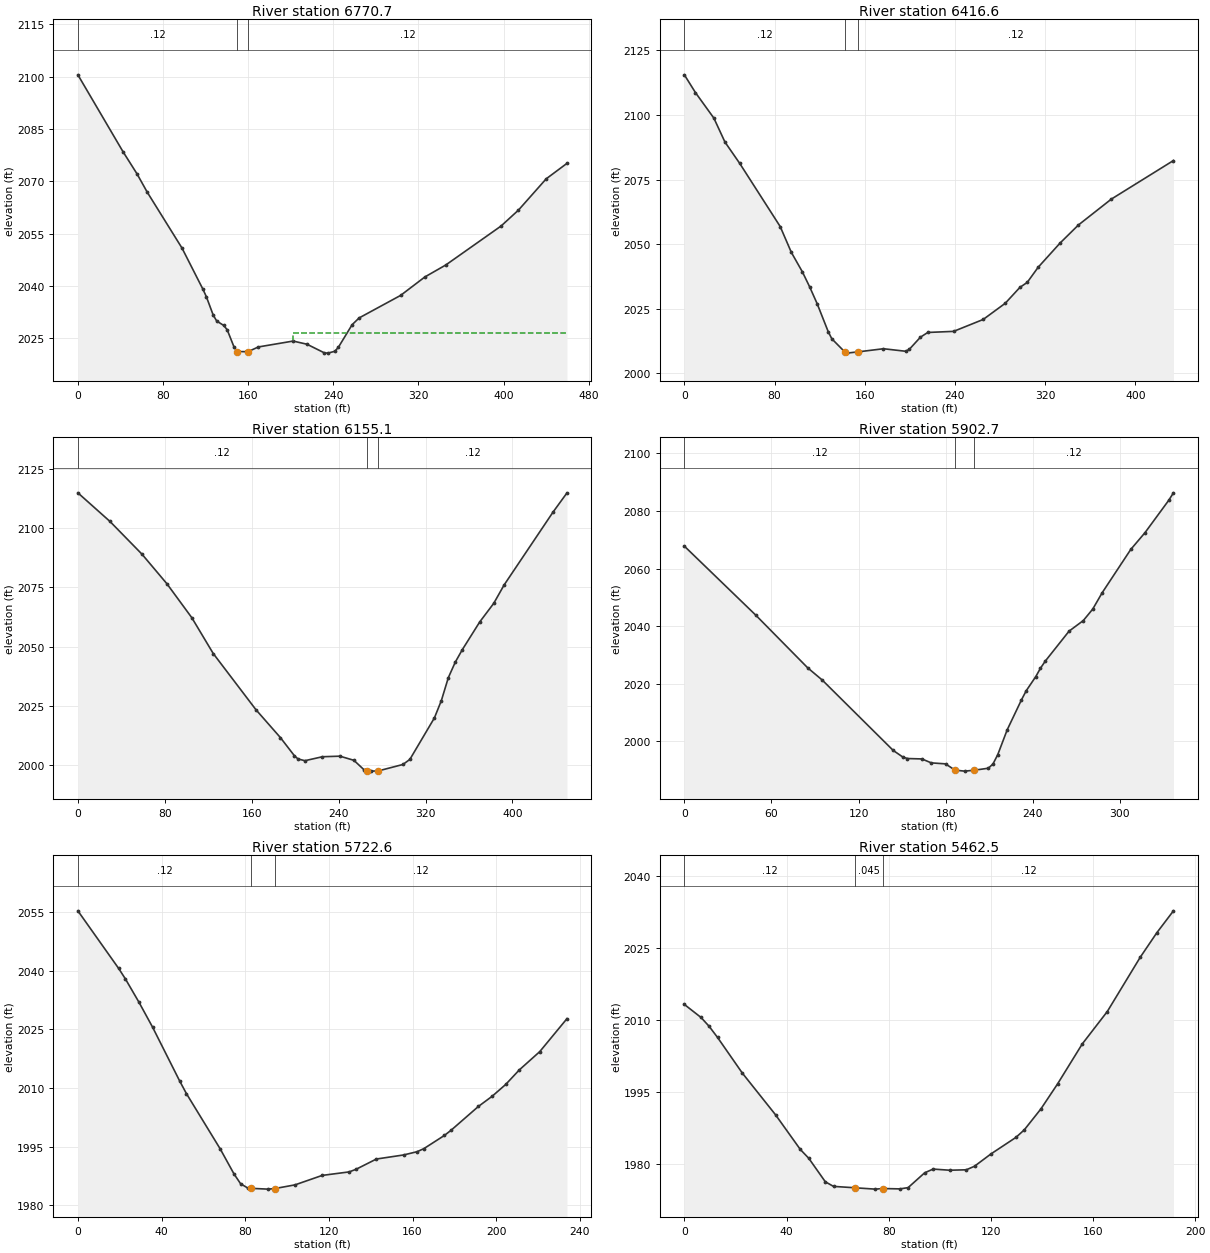
Type RM Length L Ch R = 1 ,6770.7  ,387.2,354,320.5
XS GIS Cut Line= 3
     1964443.719      231921.878     1964489.292      231654.951
     1964411.167      231483.076
#Sta/Elev= 30
       0 2100.49    42.4 2078.46    55.5 2072.14    65.2 2066.84    97.9  2050.8
   117.4  2039.1   120.7 2036.92   127.2  2031.6   130.5  2029.9     137 2028.66
   140.3 2027.42   146.8 2022.42   149.82021.157   159.9 2021.13   169.6 2022.48
   202.3 2024.17   215.3 2023.26   231.6 2020.79   234.9 2020.71   241.4 2021.23
   244.7 2022.34   257.7 2028.85   264.3  2030.8   303.3 2037.26   326.1 2042.55
   345.7 2045.97   397.7 2057.15     414  2061.7   440.1 2070.68   459.6 2075.11
#Mann= 3 ,-1 , 0
       0     .12       0   149.8    .045       0   159.9     .12       0
#XS Ineff= 2 , 0
                          202.27         2026.59
Permanent Ineff=
       F       F
Bank Sta=149.8,159.9
XS Rating Curve= 0 ,0
Exp/Cntr=0.3,0.1

Type RM Length L Ch R = 1 ,6416.6  ,261.2,261.5,257.6
XS GIS Cut Line= 3
     1964868.198      231628.909     1964593.458       231554.69
     1964484.083      231453.128
#Sta/Elev= 30
       0 2115.57     9.8 2108.72    26.2 2098.79      36 2089.55    49.1 2081.29
      85 2056.85    94.9 2046.84   104.7 2039.29   111.2 2033.44   117.8 2026.97
   127.6 2016.15   130.8  2013.4  142.312008.317   143.9 2007.86   153.7 2008.33
   176.6 2009.56   196.3 2008.58   199.5 2009.32   209.4 2014.04   215.9 2015.86
   238.8 2016.28     265 2020.88   284.6 2027.15   297.6  2033.3   304.1 2035.23
   313.8 2041.09   333.3 2050.49   349.5 2057.45   378.7 2067.47   433.8  2082.4
#Mann= 3 ,-1 , 0
       0     .12       0  142.31    .045       0   153.7     .12       0
Bank Sta=142.31,153.7
XS Rating Curve= 0 ,0
Exp/Cntr=0.3,0.1

Type RM Length L Ch R = 1 ,6155.1  ,232.9,252.4,269.9
XS GIS Cut Line= 4
     1964953.528      231500.784      1964836.34      231386.201
      1964680.09      231347.138     1964591.549      231258.597
#Sta/Elev= 30
       0 2114.82    29.5 2102.79      59 2088.99      82 2076.51   104.9 2062.22
   124.6 2047.16   163.9  2023.5   186.4 2011.77   199.3 2004.12   202.6 2002.76
     209 2002.02   225.1 2003.69   241.2 2003.93   254.1 2002.18   263.8 1998.03
   265.91997.786   270.2 1997.63   276.6 1997.73   299.2 2000.43   305.6 2002.57
   328.2 2020.05   334.6 2027.35     341 2036.98   347.4 2043.52   353.8 2048.72
   369.9 2060.45   382.8 2068.28   392.4 2076.06   437.3 2106.65   450.2 2114.78
#Mann= 3 ,-1 , 0
       0     .12       0   265.9    .045       0   276.6     .12       0
Bank Sta=265.9,276.6
XS Rating Curve= 0 ,0
Exp/Cntr=0.3,0.1

Type RM Length L Ch R = 1 ,5902.7  ,172.9,180.1,186.8
XS GIS Cut Line= 2
      1964992.59       231373.18     1964828.528      231078.909
#Sta/Elev= 30
       0 2067.76    49.1 2043.87      85 2025.53    94.9 2021.35   143.9 1996.88
   150.5  1994.6   153.7 1994.09   163.6 1993.95   170.1 1992.58   179.9 1992.24
   186.4 1990.07     193 1989.72   199.5 1990.02   209.4 1990.73   212.6 1992.21
   215.9 1995.47   222.4 2004.08   232.2 2014.44   235.5 2017.62   242.1 2022.54
   245.3 2025.42   248.6 2027.88     265 2038.28   274.8 2041.95   281.3 2045.93
   287.8  2051.6   307.5 2066.63   317.3 2072.44   333.6 2083.63   336.9 2086.26
#Mann= 3 ,-1 , 0
       0     .12       0   186.4    .045       0   199.5     .12       0
Bank Sta=186.4,199.5
XS Rating Curve= 0 ,0
Exp/Cntr=0.3,0.1

Type RM Length L Ch R = 1 ,5722.6  ,273,260.1,246
XS GIS Cut Line= 3
     1965092.156      231264.326     1965059.604      231105.472
     1965027.052       231041.67
#Sta/Elev= 30
       0 2055.35    19.5 2040.61    22.7 2037.95    29.2 2031.97    35.7  2025.6
    48.6 2011.88    51.9 2008.58    68.1 1994.39    74.6 1988.07    77.8 1985.52
    81.1 1984.47   82.941984.349    90.8 1984.15      94 1984.28   103.8 1985.24
   116.8 1987.66   129.7 1988.56     133 1989.23   142.7 1991.85   155.7 1992.89
   162.2 1993.73   165.4 1994.51   175.2 1997.88   178.4 1999.21   191.5 2005.32
     198 2007.89   204.5 2010.92     211 2014.64   220.8 2019.33   233.8 2027.76
#Mann= 3 ,-1 , 0
       0     .12       0   82.94    .045       0      94     .12       0
Bank Sta=82.94,94
XS Rating Curve= 0 ,0
Exp/Cntr=0.3,0.1

Type RM Length L Ch R = 1 ,5462.5  ,233.9,235.8,237.3
XS GIS Cut Line= 2
     1965318.719      231065.107        1965182.      230930.992
#Sta/Elev= 30
       0 2013.26     6.5 2010.56     9.7 2008.71      13 2006.39    22.7 1998.98
    35.7 1990.31    45.4  1983.1    48.7 1981.27    55.2 1976.37    58.4 1975.42
    66.8 1975.13    74.7 1974.85    77.9 1974.97    84.4  1974.9    87.6 1975.16
    94.1 1978.25    97.4 1979.02   103.9 1978.78   110.4 1978.87   113.6 1979.61
   120.1 1982.19   129.8  1985.6   133.1 1987.18   139.6 1991.53   146.1 1996.71
   155.8 2005.05   165.6 2011.79   178.5 2023.08     185 2028.18   191.5 2032.73
#Mann= 3 ,-1 , 0
       0     .12       0    66.8    .045       0    77.9     .12       0
Bank Sta=66.8,77.9
XS Rating Curve= 0 ,0
Exp/Cntr=0.3,0.1

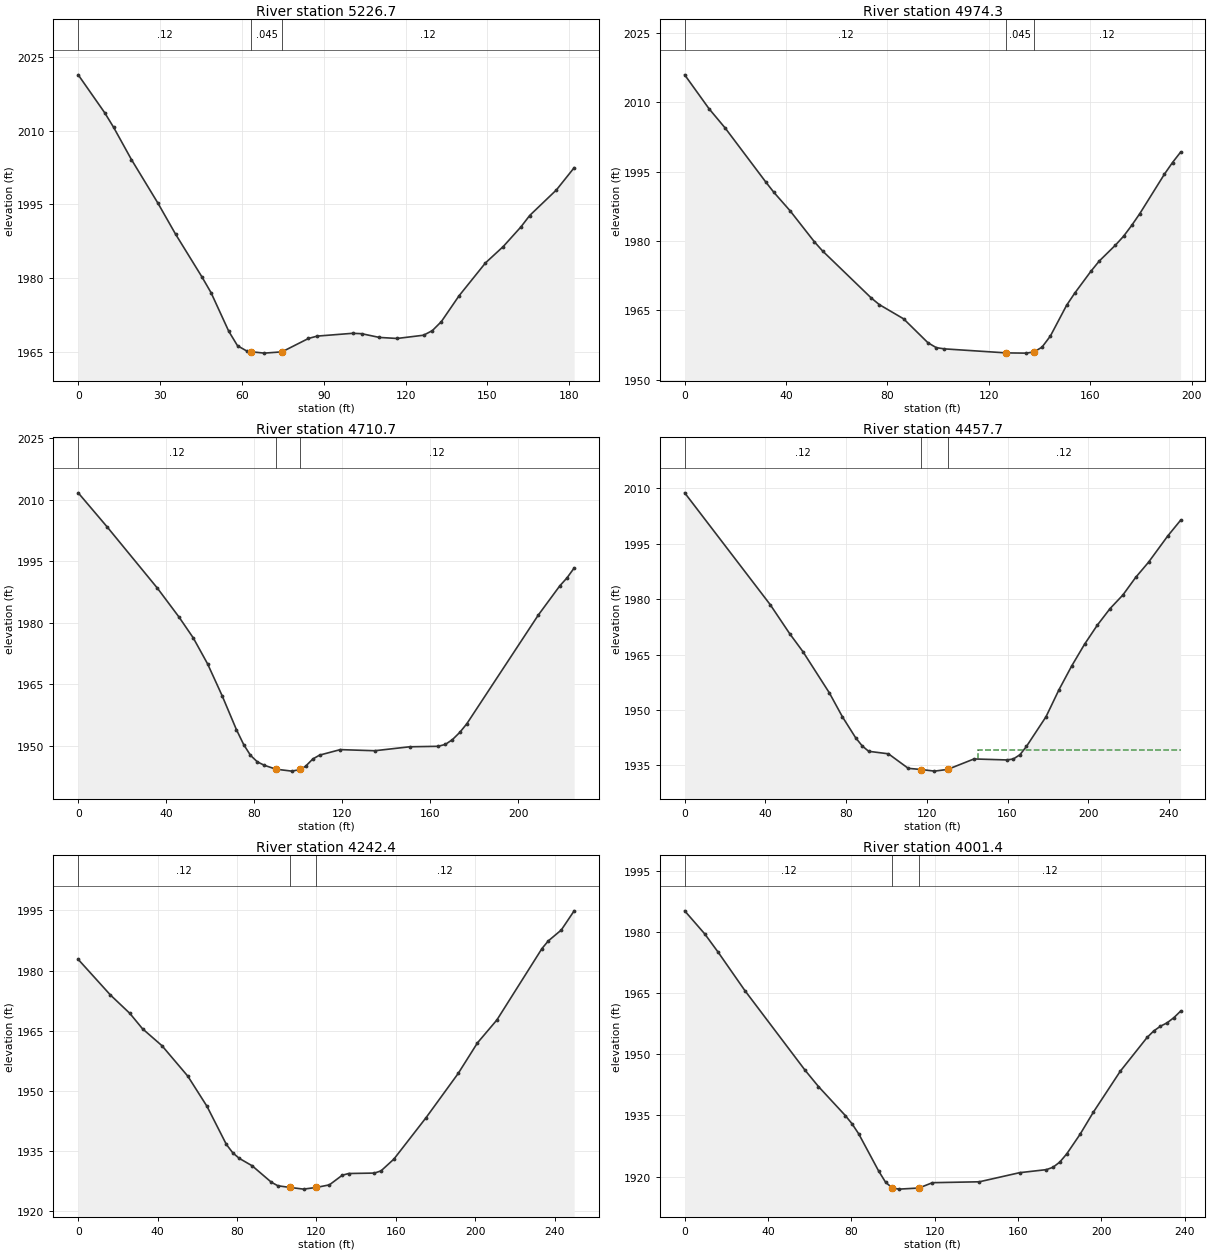
Type RM Length L Ch R = 1 ,5226.7  ,250,252.4,253.3
XS GIS Cut Line= 2
     1965497.104      230921.878     1965377.312      230785.159
#Sta/Elev= 30
       0 2021.34     9.7 2013.64      13 2010.65    19.5 2004.13    29.2 1995.28
    35.7 1988.95    45.4 1980.23    48.7 1977.06    55.2 1969.21    58.4 1966.28
    61.7 1965.24   63.431965.056    68.2 1964.78    74.7 1965.04    84.4 1967.76
    87.6 1968.24   100.6 1968.81   103.9 1968.73   110.4 1967.97   116.9 1967.76
   126.6 1968.42   129.8 1969.35   133.1 1971.17   139.6 1976.43   149.3 1983.12
   155.8 1986.44   162.3 1990.44   165.5 1992.75   175.3 1997.95   181.8 2002.46
#Mann= 3 ,-1 , 0
       0     .12       0   63.43    .045       0    74.7     .12       0
Bank Sta=63.43,74.7
XS Rating Curve= 0 ,0
Exp/Cntr=0.3,0.1

Type RM Length L Ch R = 1 ,4974.3  ,252,263.6,275
XS GIS Cut Line= 3
     1965662.469      230792.972     1965637.729      230713.545
     1965570.021      230623.701
#Sta/Elev= 30
       0  2015.9     9.6 2008.58      16 2004.39      32 1992.74    35.2  1990.5
    41.6 1986.51    51.2  1979.8    54.4 1977.84    73.6 1967.68    76.8 1966.24
    86.4 1963.16      96 1957.99    99.3 1956.93   102.5 1956.67   126.9  1955.8
   134.6 1955.75   137.8 1955.99     141 1957.04   144.3 1959.44   150.7 1966.08
   153.9  1968.7   160.3 1973.44   163.6 1975.66     170  1979.1   173.2 1981.02
   176.4 1983.36   179.6 1985.91   189.3 1994.42   192.5 1996.95   195.7  1999.2
#Mann= 3 ,-1 , 0
       0     .12       0   126.9    .045       0   137.8     .12       0
Bank Sta=126.9,137.8
XS Rating Curve= 0 ,0
Exp/Cntr=0.3,0.1

Type RM Length L Ch R = 1 ,4710.7  ,248.6,253,256.3
XS GIS Cut Line= 4
     1965859.083      230694.013     1965840.854      230621.097
     1965831.739      230549.482     1965797.885       230479.17
#Sta/Elev= 30
       0 2011.65    13.1 2003.38      36 1988.41    45.8 1981.39    52.3 1976.29
    58.8 1969.97    65.4 1962.22    71.9 1953.95    75.2 1950.31    78.3 1947.68
    81.4  1946.1    84.6 1945.25    89.9  1944.3    97.1 1943.83     1011944.237
   103.4 1945.05   106.6 1946.78   109.7 1947.73   119.1 1949.07   134.8  1948.8
   150.6 1949.76   163.6 1949.88   166.9 1950.35   170.1 1951.52   173.4 1953.26
   176.6 1955.36   209.1 1981.86   218.9    1989   222.1 1990.89   225.4 1993.33
#Mann= 3 ,-1 , 0
       0     .12       0    89.9    .045       0     101     .12       0
Bank Sta=89.9,101
XS Rating Curve= 0 ,0
Exp/Cntr=0.3,0.1

Type RM Length L Ch R = 1 ,4457.7  ,224.2,215.2,205.5
XS GIS Cut Line= 3
     1966071.323       230648.44     1966079.135      230472.659
     1966068.719      230403.649
#Sta/Elev= 30
       0 2008.82    42.4 1978.52    52.1 1970.62    58.6  1965.8    71.7 1954.63
    78.2 1948.12    84.7 1942.49      88 1940.24    91.2 1938.79     101 1938.11
   110.8 1934.18   117.3 1933.85   123.8 1933.42   130.3 1933.88   143.4 1936.72
   159.7 1936.45   162.9 1936.71   166.2 1937.88   169.4 1940.12   179.1 1948.17
   185.5 1955.46   191.8  1961.9   198.2 1967.81   204.5 1972.96   210.8 1977.44
   217.2 1981.15   223.5 1985.89   229.9 1990.02   239.4 1997.12   245.8  2001.4
#Mann= 3 ,-1 , 0
       0     .12       0   117.3    .045       0   130.3     .12       0
#XS Ineff= 2 , 0
                          145.51         1939.09
Permanent Ineff=
       F       F
Bank Sta=117.3,130.3
XS Rating Curve= 0 ,0
Exp/Cntr=0.3,0.1

Type RM Length L Ch R = 1 ,4242.4  ,242.4,241.1,234.4
XS GIS Cut Line= 2
     1966322.625      230593.753     1966232.781       230360.68
#Sta/Elev= 30
       0 1982.78    16.2 1973.92      26 1969.33    32.4 1965.49    42.2 1961.27
    55.2 1953.69    64.9 1946.14    74.6  1936.7    77.9 1934.56    81.1 1933.21
    87.6 1931.36    97.3 1927.25   100.6 1926.37   106.9 1925.95   113.5 1925.54
     120 1925.97   126.5  1926.6     133    1929   136.2 1929.43   149.2 1929.54
   152.5 1930.08     159 1933.02   175.2 1943.34   191.4 1954.37   201.1 1961.98
   210.9  1967.7   233.6 1985.49   236.8  1987.4   243.3 1990.09   249.8 1994.88
#Mann= 3 ,-1 , 0
       0     .12       0   106.9    .045       0     120     .12       0
Bank Sta=106.9,120
XS Rating Curve= 0 ,0
Exp/Cntr=0.3,0.1

Type RM Length L Ch R = 1 ,4001.4  ,252.3,252.2,253.3
XS GIS Cut Line= 3
     1966521.844      230503.909     1966506.219      230415.367
     1966422.885      230292.972
#Sta/Elev= 30
       0 1985.16     9.6 1979.52    16.1 1974.99    28.9  1965.6    57.8 1946.06
    64.2 1942.08    77.1 1934.96    80.3 1932.95    83.5 1930.49    93.1 1921.35
    96.4 1918.62    99.6 1917.22   102.8 1916.92   112.4 1917.19   118.9  1918.5
   141.4 1918.72   160.7 1920.95   173.6  1921.7   176.8 1922.29     180 1923.55
   183.3 1925.53   189.7 1930.33   196.1 1935.77     209  1945.8   221.9  1954.1
   225.1  1955.7   228.3 1956.86   231.5 1957.69   234.8 1958.98     238 1960.57
#Mann= 3 ,-1 , 0
       0     .12       0    99.6    .045       0   112.4     .12       0
Bank Sta=99.6,112.4
XS Rating Curve= 0 ,0
Exp/Cntr=0.3,0.1

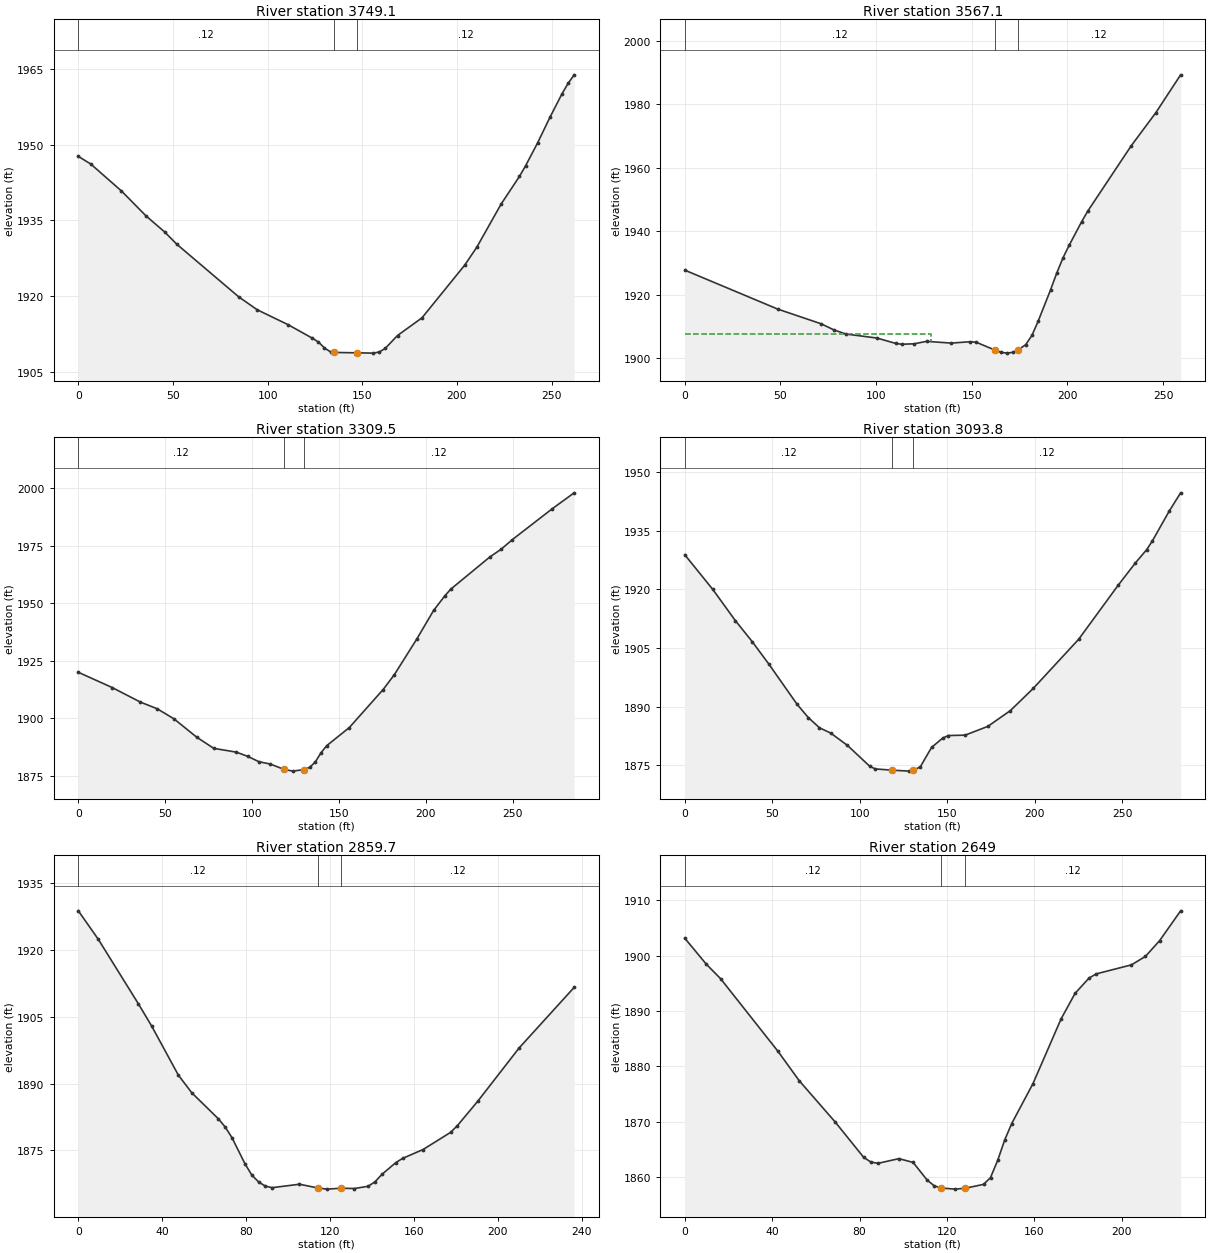
Type RM Length L Ch R = 1 ,3749.1  ,169.7,182.1,194
XS GIS Cut Line= 3
     1966717.156       230385.42     1966696.323      230279.951
     1966622.104      230144.534
#Sta/Elev= 30
       0 1947.69     6.5  1946.2    22.8 1940.84    35.8 1935.89    45.6 1932.73
    52.1 1930.27    84.7 1919.89    94.5 1917.32   110.7 1914.39   123.6  1911.7
   126.8 1910.95     130 1909.77   133.2 1908.99  134.821908.877   147.3  1908.8
   155.8 1908.74     159 1908.97   162.2 1909.71   168.6 1912.23   181.5 1915.72
     204 1926.12   210.4 1929.66   223.3 1938.24     233 1943.73   236.2  1945.8
   242.6 1950.37   249.1 1955.42   255.5  1960.1   258.7 1962.15   261.9 1963.84
#Mann= 3 ,-1 , 0
       0     .12       0  134.82    .045       0   147.3     .12       0
Bank Sta=134.82,147.3
XS Rating Curve= 0 ,0
Exp/Cntr=0.3,0.1

Type RM Length L Ch R = 1 ,3567.1  ,247.5,257.6,265.7
XS GIS Cut Line= 2
     1966823.927      230320.315     1966831.739      230061.201
#Sta/Elev= 30
       0 1927.75    48.6 1915.47    71.3 1910.84    77.8 1908.96    84.2 1907.62
   100.4 1906.36   110.2 1904.68   113.4  1904.4   119.9 1904.54   126.4 1905.31
   139.3 1904.76   149.1 1905.19   152.3 1905.04     162  1902.6   165.3 1901.86
   168.5  1901.6   171.7 1901.87  174.071902.531   178.2 1904.26   181.5 1907.21
   184.7 1911.63   191.2 1921.52   194.4 1926.76   197.7 1931.62   200.9 1935.55
   207.4 1942.95   210.6  1946.3   233.3 1966.88   246.3 1977.42   259.2  1989.3
#Mann= 3 ,-1 , 0
       0     .12       0     162    .045       0  174.07     .12       0
#XS Ineff= 2 , 0
          128.48 1907.77
Permanent Ineff=
       F       F
Bank Sta=162,174.07
XS Rating Curve= 0 ,0
Exp/Cntr=0.3,0.1

Type RM Length L Ch R = 1 ,3309.5  ,229.1,215.7,201.1
XS GIS Cut Line= 3
     1966991.896      230356.774     1967071.323      230182.295
     1967049.187      230091.149
#Sta/Elev= 30
       0 1919.98    19.5 1913.34    35.7 1907.02    45.5 1904.07    55.2 1899.65
    68.2 1891.71      78 1886.87      91 1885.22    97.5  1883.4     104 1881.05
   110.5 1880.05  118.341877.758   123.5 1876.96     130 1877.65   133.2 1878.57
   136.5 1881.01   139.7 1884.91     143 1888.03     156  1895.9   175.5 1912.47
     182 1918.98   194.9 1934.47   204.6 1946.94   211.1  1953.3   214.4 1956.13
     237 1970.21   243.5 1973.56   249.9 1977.72   272.6    1991   285.5 1998.09
#Mann= 3 ,-1 , 0
       0     .12       0  118.34    .045       0     130     .12       0
Bank Sta=118.34,130
XS Rating Curve= 0 ,0
Exp/Cntr=0.3,0.1

Type RM Length L Ch R = 1 ,3093.8  ,263.2,234.1,198.1
XS GIS Cut Line= 4
     1967303.094      230315.107     1967256.219      230246.097
     1967241.896      230170.576     1967145.542      230093.753
#Sta/Elev= 30
       0 1928.82      16 1919.97    28.9 1911.99    38.5 1906.64    48.1 1900.84
    64.2 1890.58    70.6  1887.2      77 1884.58    83.4 1883.23      93 1880.07
   105.8 1874.71     109 1874.05   118.7 1873.73   128.3 1873.49   130.6 1873.66
   134.7 1874.62   141.1 1879.56   147.5 1881.95   150.7 1882.59   160.3 1882.69
   173.3 1884.94   186.2 1888.99   199.2 1894.63   225.2 1907.21   247.8 1921.04
   257.6 1926.72   264.1 1930.14   267.3 1932.34     277 1940.01   283.5 1944.67
#Mann= 3 ,-1 , 0
       0     .12       0   118.7    .045       0   130.6     .12       0
Bank Sta=118.7,130.6
XS Rating Curve= 0 ,0
Exp/Cntr=0.3,0.1

Type RM Length L Ch R = 1 ,2859.7  ,182.9,210.7,240.5
XS GIS Cut Line= 3
     1967439.812      230106.774       1967369.5      230052.086
     1967222.364       230048.18
#Sta/Elev= 30
       0 1928.81     9.5 1922.42    28.6 1907.94      35 1902.88    47.7 1891.88
    54.1 1887.92    66.8 1882.06      70 1880.24    73.2 1877.87    79.5 1871.91
    82.7 1869.44    85.9 1867.91    89.1 1866.97    92.4 1866.62   105.4 1867.39
  114.371866.532   118.5 1866.29   125.1 1866.49   131.6 1866.43   138.1 1866.93
   141.4 1867.94   144.7 1869.61   151.2 1872.21   154.5 1873.19   164.3 1875.19
   177.4 1879.04   180.7 1880.58   190.5 1886.12   210.1 1898.02   236.3 1911.61
#Mann= 3 ,-1 , 0
       0     .12       0  114.37    .045       0   125.1     .12       0
Bank Sta=114.37,125.1
XS Rating Curve= 0 ,0
Exp/Cntr=0.3,0.1

Type RM Length L Ch R = 1 ,2649    ,227.5,221.2,213.8
XS GIS Cut Line= 3
     1967536.167      229989.586     1967473.667      229927.086
     1967422.885       229798.18
#Sta/Elev= 30
       0 1903.17     9.8  1898.5    16.4 1895.85    42.6 1882.76    52.4 1877.41
    68.8 1869.98    81.8 1863.61    85.1 1862.74    88.4  1862.5      98 1863.35
   104.5 1862.66   110.9 1859.48   114.2 1858.42   117.4 1858.04   123.8 1857.84
  128.431858.004   136.7  1858.7   139.9 1859.92   143.2 1863.06   146.4 1866.72
   149.6 1869.69   159.3 1876.88   172.2  1888.6   178.6 1893.21     185 1895.98
   188.3 1896.73   204.4 1898.36   210.8 1899.89   217.3 1902.74   226.9 1908.12
#Mann= 3 ,-1 , 0
       0     .12       0   117.4    .045       0  128.43     .12       0
Bank Sta=117.4,128.43
XS Rating Curve= 0 ,0
Exp/Cntr=0.3,0.1

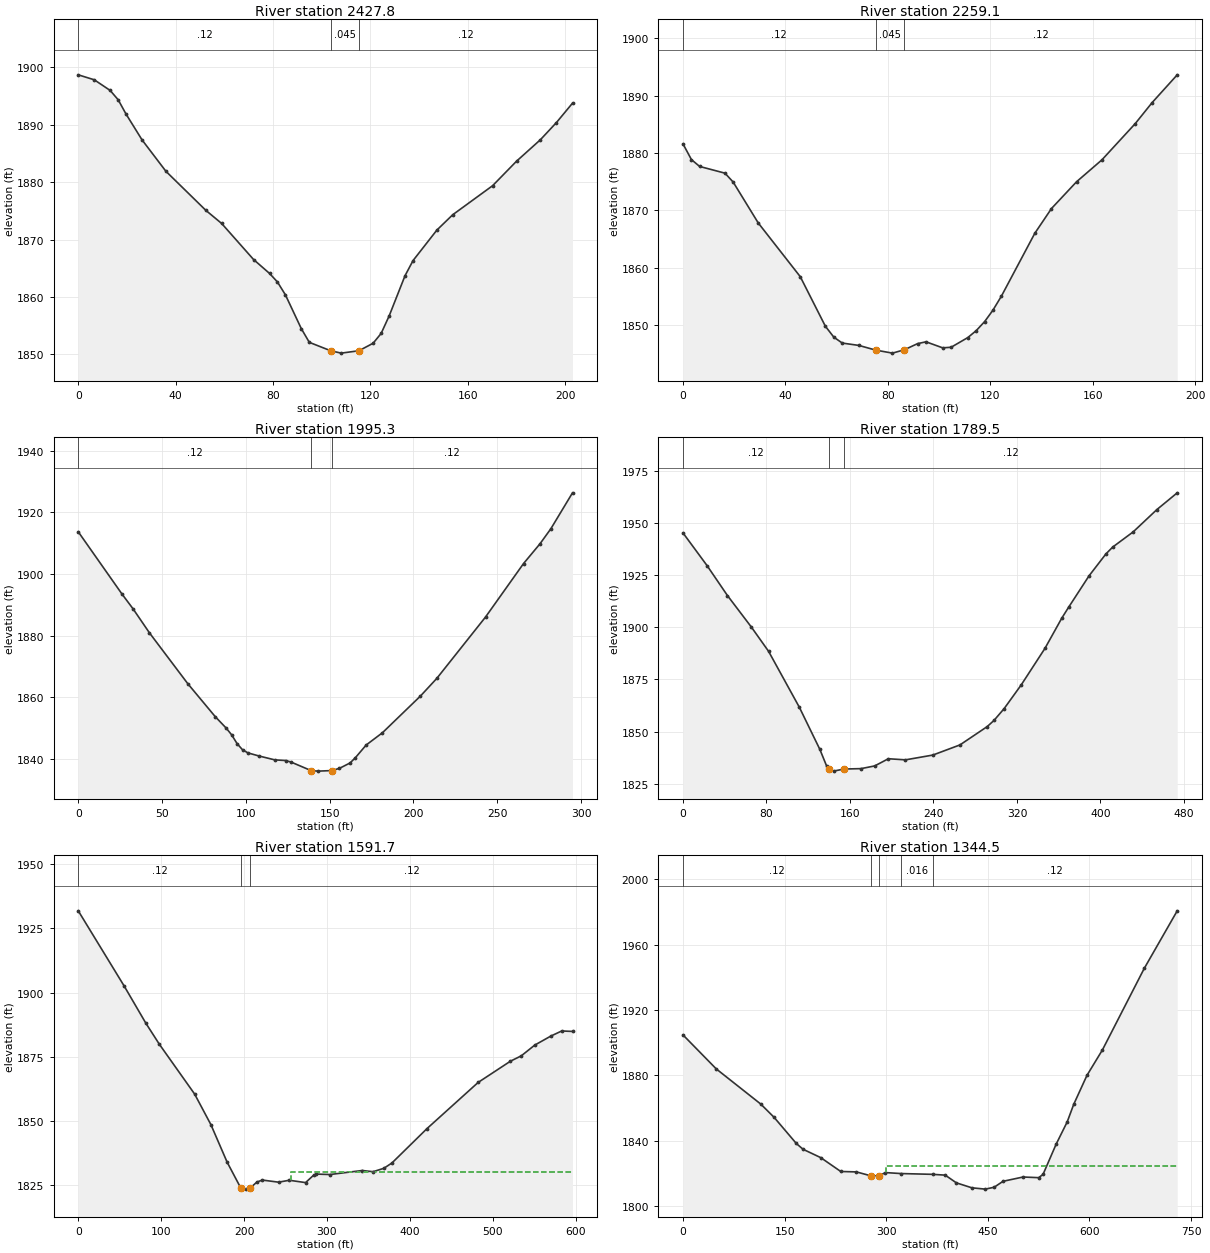
Type RM Length L Ch R = 1 ,2427.8  ,173.7,168.7,162.9
XS GIS Cut Line= 2
     1967696.323      229871.097     1967570.021      229712.242
#Sta/Elev= 30
       0 1898.71     6.6 1897.84    13.1 1895.99    16.4 1894.36    19.6 1891.89
    26.2 1887.37      36  1881.9    52.4 1875.09    58.9  1872.8      72 1866.52
    78.6 1864.08    81.8 1862.61    85.1 1860.35    91.6 1854.48    94.9 1852.08
   103.7 1850.61     108  1850.2  115.281850.615   121.1 1851.92   124.4 1853.63
   127.7 1856.69   134.2 1863.68   137.5 1866.33   147.3 1871.65   153.8 1874.32
   170.2 1879.39     180 1883.65   189.8 1887.39   196.4 1890.39     203 1893.77
#Mann= 3 ,-1 , 0
       0     .12       0   103.7    .045       0  115.28     .12       0
Bank Sta=103.7,115.28
XS Rating Curve= 0 ,0
Exp/Cntr=0.3,0.1

Type RM Length L Ch R = 1 ,2259.1  ,251.6,263.7,274.7
XS GIS Cut Line= 2
     1967808.302      229716.149     1967655.958      229597.659
#Sta/Elev= 30
       0 1881.59     3.3 1878.85     6.5 1877.66    16.4 1876.49    19.6 1874.94
    29.4 1867.82    45.8 1858.48    55.6 1849.86    58.9 1847.96    62.2 1846.93
    68.7 1846.52    75.2 1845.71    81.8 1845.18   86.431845.763    91.6 1846.83
    94.9 1847.15   101.4  1846.1   104.7  1846.2   111.2 1847.88   114.5 1849.09
   117.8 1850.67     121 1852.63   124.3 1855.06   137.4 1866.04   143.9 1870.34
   153.7    1875   163.6 1878.81   176.6 1885.11   183.2 1888.77     193  1893.6
#Mann= 3 ,-1 , 0
       0     .12       0    75.2    .045       0   86.43     .12       0
Bank Sta=75.2,86.43
XS Rating Curve= 0 ,0
Exp/Cntr=0.3,0.1

Type RM Length L Ch R = 1 ,1995.3  ,218.8,205.8,192.4
XS GIS Cut Line= 4
     1967993.198      229591.149     1967917.677      229528.649
     1967885.125      229451.826     1967788.771       229391.93
#Sta/Elev= 30
       0 1913.72    26.1 1893.49    32.7 1888.69    42.5 1880.87    65.4 1864.34
    81.7 1853.68    88.2 1849.98    91.5 1847.77    94.8 1844.87      98 1842.91
   101.2 1841.89   107.7  1840.9   117.3 1839.61   123.7 1839.41   126.9 1838.92
  138.851836.153     143 1835.96  151.121836.134   155.8 1836.85   162.2 1838.62
   165.4 1840.35   171.8 1844.45   181.5 1848.43   204.2 1860.37   213.9 1866.07
     243 1886.02   265.7 1903.41   275.5 1909.82     282 1914.72   294.9 1926.38
#Mann= 3 ,-1 , 0
       0     .12       0  138.85    .045       0  151.12     .12       0
Bank Sta=138.85,151.12
XS Rating Curve= 0 ,0
Exp/Cntr=0.3,0.1

Type RM Length L Ch R = 1 ,1789.5  ,193.4,197.8,200.5
XS GIS Cut Line= 3
     1968189.812      229455.732     1967990.594       229322.92
     1967760.125      229281.253
#Sta/Elev= 30
       0 1945.17      23 1929.56    42.6 1915.18    65.6 1900.03      82 1888.48
   111.5 1861.69   131.2 1841.46   137.8 1833.35  140.081831.918   144.3  1831.1
   154.2  1832.1   170.6  1832.3   183.7 1833.59   196.8 1837.03   213.2  1836.5
   239.4 1838.79   265.4 1843.65   291.5 1852.42     298 1855.37   307.7 1861.01
     324 1872.31   346.8 1889.84     363 1904.38   369.5 1909.55   389.1 1924.62
   405.3 1935.12   411.8  1938.4   431.4 1945.66   454.1 1956.34   473.6 1964.36
#Mann= 3 ,-1 , 0
       0     .12       0  140.08    .045       0   154.2     .12       0
Bank Sta=140.08,154.2
XS Rating Curve= 0 ,0
Exp/Cntr=0.3,0.1

Type RM Length L Ch R = 1 ,1591.7  ,246.1,247.1,247.7
XS GIS Cut Line= 3
     1968297.885      229342.451     1968077.833      229138.024
      1967782.26      229125.003
#Sta/Elev= 30
       0 1931.81    55.5 1902.48    81.6 1888.04    97.9 1879.84   140.4 1860.48
     160 1848.59   179.6 1833.97   195.9 1824.01   202.4 1823.48   207.6 1823.99
   215.5 1826.23     222 1827.01   241.6 1826.19   254.6 1826.93   274.2 1826.02
     284 1828.92   287.3 1829.34   303.6 1829.16   342.6 1830.73   355.6 1830.26
   368.6 1831.58   378.4 1833.66   420.6 1847.02   482.4 1865.02   521.4 1873.29
   534.4 1875.36   550.7 1879.55   570.2 1883.08   583.2 1885.04   596.2 1884.87
#Mann= 3 ,-1 , 0
       0     .12       0   195.9    .045       0   207.6     .12       0
#XS Ineff= 2 , 0
                          256.97         1830.14
Permanent Ineff=
       F       F
Bank Sta=195.9,207.6
XS Rating Curve= 0 ,0
Exp/Cntr=0.3,0.1

Type RM Length L Ch R = 1 ,1344.5  ,450.8,436.3,420
XS GIS Cut Line= 3
      1968501.01      229213.545     1968133.823      228847.659
     1968050.489      228653.649
#Sta/Elev= 30
       0 1904.73    49.2 1883.86   114.8 1862.34   134.5  1854.2   167.3 1838.17
   177.2 1834.64   203.4 1829.49   232.9 1821.01   255.9 1820.76   277.7 1818.31
  290.051818.435   298.6 1820.35  321.521819.749  368.581819.263   387.1 1818.77
   403.5 1814.05   426.5    1811   446.2  1810.2   459.3 1811.36   472.4    1815
     502 1817.63   524.9 1817.23   531.4 1819.19   550.8 1837.78   567.1 1851.42
   576.8 1862.24   596.3 1879.96   619.1 1895.54   680.8 1945.49   729.5 1980.79
#Mann= 5 ,-1 , 0
       0     .12       0   277.7    .045       0  290.05     .12       0
  321.52    .016       0  368.58     .12       0
#XS Ineff= 2 , 0
                          299.69         1824.66
Permanent Ineff=
       F       F
Bank Sta=277.7,290.05
XS Rating Curve= 0 ,0
Exp/Cntr=0.3,0.1

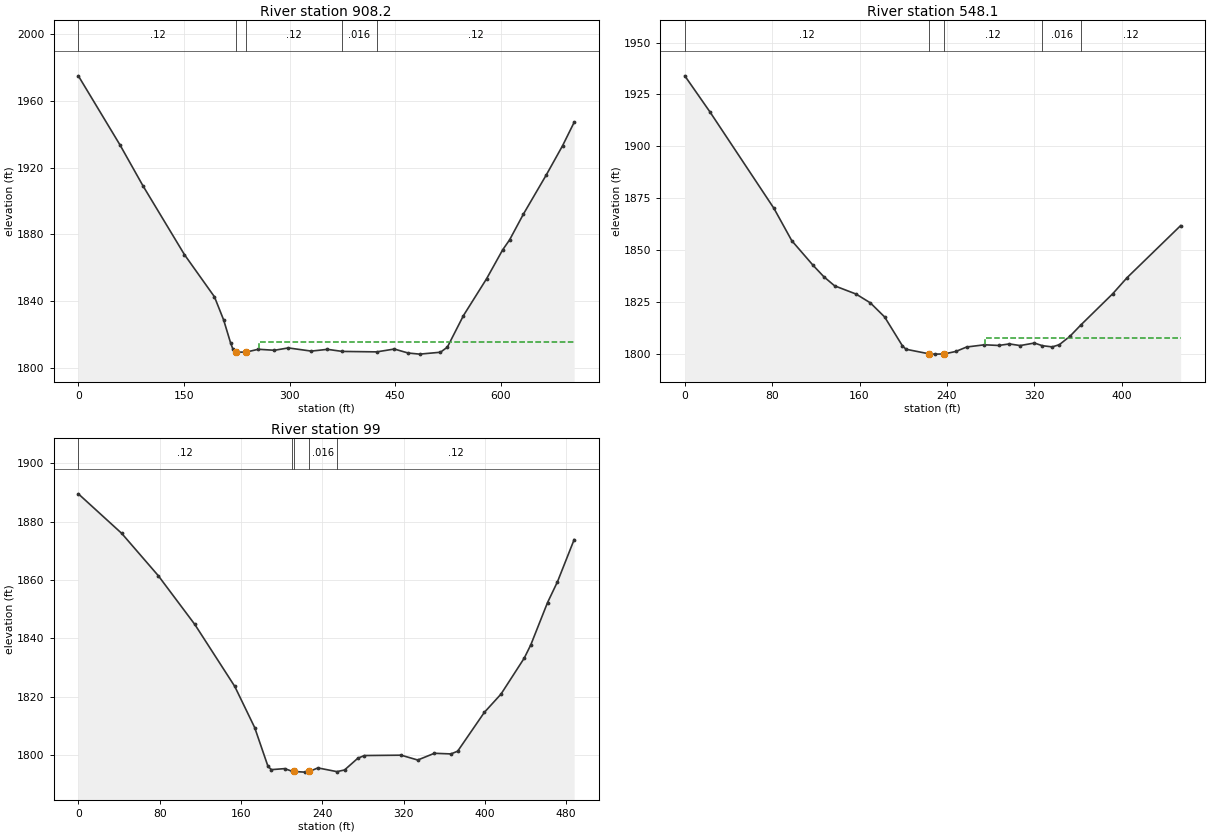
Type RM Length L Ch R = 1 ,908.2   ,354.1,360,363
XS GIS Cut Line= 3
     1968843.458      228757.815     1968524.448      228721.357
     1968191.114      228532.555
#Sta/Elev= 30
       0 1974.84      59 1933.64    91.7 1909.14   150.7 1867.93   193.3 1842.71
   206.4 1828.84   216.2 1815.18   219.5 1811.46  224.571809.612  238.171809.608
   255.6 1811.33   278.5 1810.72   298.2 1812.13   330.9 1810.23   353.8 1811.28
  374.851810.044  423.751809.767   448.8 1811.46   468.4 1809.08   484.8 1808.42
   514.3 1809.55   524.1 1812.59     547  1831.5   579.8 1853.48   602.7 1870.81
   612.5 1876.75   632.1 1892.14   664.9 1915.79   687.8  1933.1   704.2 1947.05
#Mann= 5 ,-1 , 0
       0     .12       0  224.57    .045       0  238.17     .12       0
  374.85    .016       0  423.75     .12       0
#XS Ineff= 2 , 0
                          256.76         1815.81
Permanent Ineff=
       F       F
Bank Sta=224.57,238.17
XS Rating Curve= 0 ,0
Exp/Cntr=0.3,0.1

Type RM Length L Ch R = 1 ,548.1   ,450.5,449.1,447.4
XS GIS Cut Line= 2
      1968813.51      228466.149     1968373.406       228354.17
#Sta/Elev= 30
       0    1934    22.9 1916.71    81.7 1870.06      98 1854.51   117.6 1842.59
   127.4 1837.12   137.2 1832.77   156.8 1828.81   169.9 1824.57     183 1817.77
   199.3 1803.85   202.6 1802.19  224.091799.937   228.7 1799.84   237.5 1799.92
   248.3 1801.14   258.1 1803.27   274.4 1804.34   287.5 1804.02   297.3 1804.76
   307.1 1803.97   320.2 1805.19  327.451803.905   336.5 1803.33     343 1804.38
   352.8 1808.49   362.81813.939     392    1829   405.1 1836.73   454.1 1861.79
#Mann= 5 ,-1 , 0
       0     .12       0  224.09    .045       0   237.5     .12       0
  327.45    .016       0   362.8     .12       0
#XS Ineff= 2 , 0
                          274.51         1807.84
Permanent Ineff=
       F       F
Bank Sta=224.09,237.5
XS Rating Curve= 0 ,0
Exp/Cntr=0.3,0.1

Type RM Length L Ch R = 1 ,99      ,97.6,99,100.1
XS GIS Cut Line= 2
     1968946.974      228023.983     1968467.156      227936.201
#Sta/Elev= 30
       0 1889.54    42.6 1876.01    78.6  1861.5   114.6 1844.76   153.9 1823.52
   173.5  1809.4   186.6  1796.1   189.9 1794.98     203 1795.33  210.041794.463
   212.3 1794.35   222.6 1794.13   227.3 1794.35   235.7 1795.58  254.391794.297
   261.9 1794.87     275  1798.9   281.5 1799.82   317.6 1799.94   333.9 1798.28
   350.3 1800.59   366.6 1800.37   373.2 1801.31   399.4  1814.6   415.8 1820.87
   438.7 1833.22   445.2 1837.82   461.6 1852.25   471.4 1859.41   487.8 1873.86
#Mann= 5 ,-1 , 0
       0     .12       0  210.04    .016       0   212.3    .045       0
   227.3    .016       0  254.39     .12       0
Bank Sta=212.3,227.3
XS Rating Curve= 0 ,0
Exp/Cntr=0.3,0.1

Chan Stop Cuts=-1
Use User Specified Reach Order=0
Composite Channel Slope=5